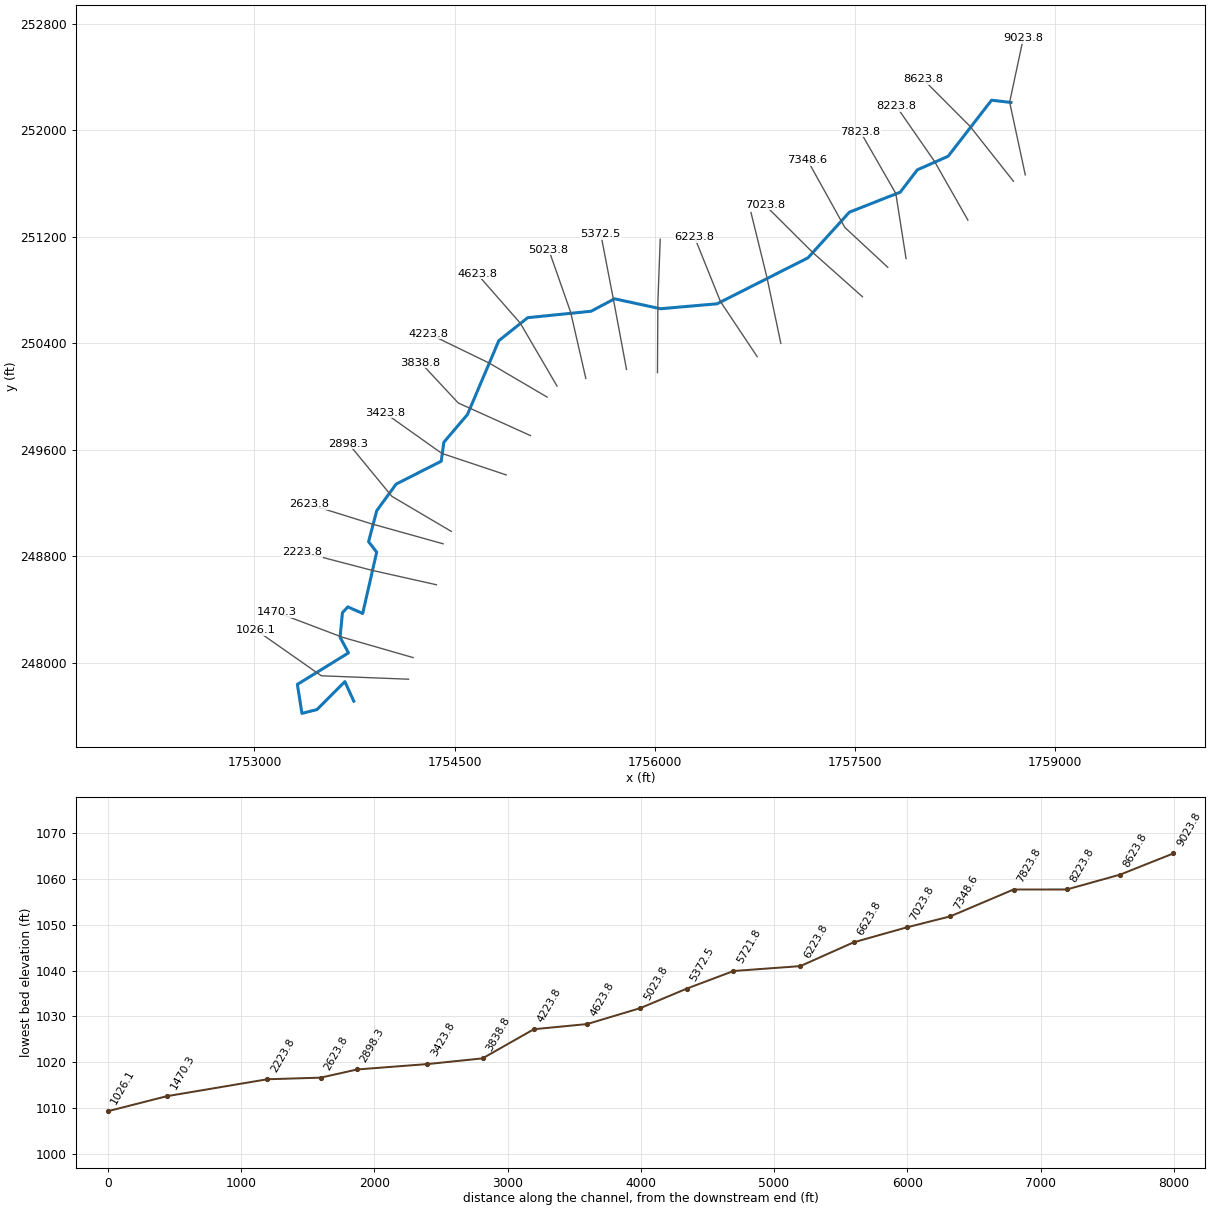
--- StoutRn.prj (project) ---

Proj Title=StoutRn
Current Plan=p01
Default Exp/Contr=0,0
English Units
Geom File=g01
Flow File=f01
Plan File=p01
BEGIN DESCRIPTION:
END DESCRIPTION:
DSS Export Rating Curves= 0
DSS Export Rating Curve Sorted= 0
DSS Export Volume Flow Curves= 0
DXF OffsetX= 0
DXF OffsetY= 0
DXF ScaleX= 0
DXF ScaleY= 0

--- StoutRn.p01 (plan) ---

Plan Title=Floodplain
Program Version=4.00
Geom File=g01
Flow File=f01
K Sum by GR=0
Std Step Tol=0.01
Critical Tol=0.01
Num of Std Step Trials=20
Max Error Tol=0.3
Flow Tol Ratio=0.001
Split Flow NTrial=30
Split Flow Tol=0.02
Split Flow Ratio=0.02
Log Output Level=0
Friction Slope Method=1
Unsteady Friction Slope Method=2
Unsteady Bridges Friction Slope Method=1
Global Log Level=0
CheckData=False
Run HTab=0
Run UNet=0
Run PostProcess=0
UNET Theta=0
UNET Theta Warmup=0
UNET ZTol=0
UNET ZSATol=0
UNET MxIter=0
UNET MaxInSteps=0
UNET DtIC=0
UNET DtMin=0
UNET MaxCRTS=0
UNET WFStab=0
UNET SFStab=0
UNET WFX=0
UNET SFX=0
UNET DSS MLevel=0
UNET DZMax Abort=0
UNET Convert EG Bridges=0
UNET Use Existing IB Tables=0
UNET Froude Limit=0
UNET Froude Power=0
Write IC File=0
Echo Input=False
Echo Output=False
Write Detailed=0

--- StoutRn.f01 (steady flow) ---

Flow Title=NFF Regression Equation
Program Version=4.00
Number of Profiles=1
Profile Names=P100yr
River Rch & RM=StoutRn,Main      ,9023.8
717.7026
River Rch & RM=StoutRn,Main      ,7348.6
759.9212
River Rch & RM=StoutRn,Main      ,7023.8
851.4480
River Rch & RM=StoutRn,Main      ,5721.8
900.3053
River Rch & RM=StoutRn,Main      ,5372.5
992.9717
River Rch & RM=StoutRn,Main      ,2898.3
1096.266
Boundary for River Rch & Prof#=StoutRn,Main      ,1
Up Type=0
Dn Type=3
Dn Slope=0.003882

--- StoutRn.g01 (geometry) ---

Geom Title=USGS 3m DEM
Program Version=4.00

River Reach=StoutRn         ,Main
Reach XY= 30
     1758669.697       252208.33     1758524.311      252225.247
     1758198.832       251804.21     1757968.054      251702.201
     1757840.055      251534.663      1757458.88      251384.314
     1757148.507       251041.38     1756467.394      250696.309
     1756043.751      250659.141     1755699.135      250733.661
     1755522.914      250640.362     1755048.139      250591.921
     1754831.883       250419.75     1754596.036      249863.752
      1754419.67      249656.584     1754400.001      249513.989
     1754062.103       249342.19     1753916.742      249142.441
     1753855.749       248909.77     1753916.284      248830.951
     1753811.449      248370.587     1753699.949      248420.236
     1753659.811      248375.945     1753641.897      248192.009
      1753704.93      248074.577     1753322.062      247837.787
     1753356.273      247620.292     1753469.314      247649.026
     1753677.969      247858.784     1753744.867      247711.782

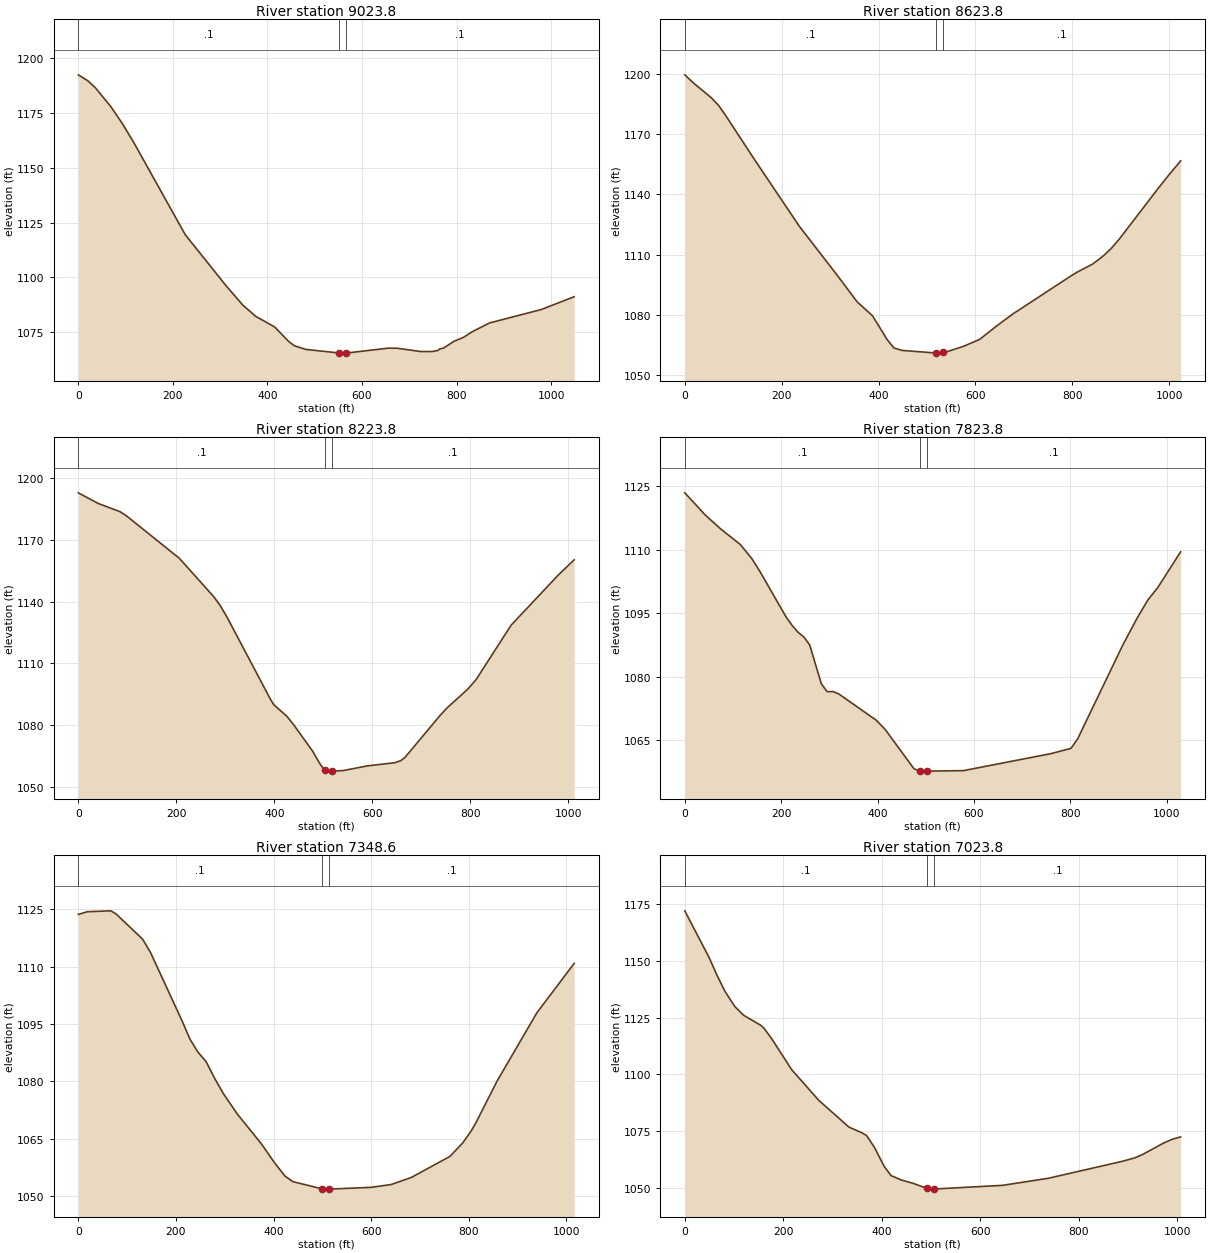
Type RM Length L Ch R = 1 ,9023.8  ,389.301,400,423.415
XS GIS Cut Line= 3
     1758777.069      251664.152     1758659.916      252210.413
     1758762.044       252689.89
#Sta/Elev= 30
       0 1192.28    19.8 1189.61    35.4 1186.55    68.4 1177.92    92.6 1170.26
   116.9 1161.61   226.2 1119.49   311.2 1096.61   347.6  1087.5   375.4 1082.29
   415.4 1077.47   444.8 1070.91   456.9 1068.92   481.2 1067.25   551.2 1065.65
   558.7 1065.56   566.2 1065.57   654.5 1067.81   674.5 1067.79     724 1066.29
   748.3 1066.29   760.4 1066.76   764.6 1067.47   772.6 1067.86   794.6 1070.94
   814.6 1072.73   833.3  1075.3   869.7 1079.29   978.9 1085.38  1048.9 1091.25
#Mann= 3 , 0 , 0
       0      .1       0   551.2    .045       0   566.2      .1       0
Bank Sta=551.2,566.2
XS Rating Curve= 0 ,0
Exp/Cntr=0.3,0.1

Type RM Length L Ch R = 1 ,8623.8  ,403.279,400,396.103
XS GIS Cut Line= 3
     1758688.331      251616.598     1758362.789      252029.227
     1758011.524      252382.374
#Sta/Elev= 30
       0 1199.58    17.5 1195.61      55 1188.09    70.1 1184.25    85.1 1179.04
   145.7 1156.73   236.4 1124.16   312.1 1100.54   355.7 1086.54   387.7 1079.49
   417.9 1067.64   431.7 1063.53   448.2 1062.29   518.1 1060.99   523.8 1060.93
   533.1 1061.26   541.5 1061.65   576.4 1064.41   608.7 1067.76   643.8 1074.46
   677.4 1080.45   795.3 1099.09   810.2 1101.29   841.7 1105.26   862.6 1109.06
   879.5 1112.84   896.3 1117.51   978.1 1143.24   997.3 1149.08  1023.7 1156.71
#Mann= 3 , 0 , 0
       0      .1       0   518.1    .045       0   533.1      .1       0
Bank Sta=518.1,533.1
XS Rating Curve= 0 ,0
Exp/Cntr=0.3,0.1

Type RM Length L Ch R = 1 ,8223.8  ,408.618,400,398.057
XS GIS Cut Line= 3
     1758347.066      251324.681      1758095.38      251768.209
     1757809.644      252181.003
#Sta/Elev= 30
       0 1192.76    40.8 1187.58    84.9 1183.64    98.6 1181.52     206 1161.01
   276.1 1142.43   289.7 1138.02   303.4 1132.46   391.2 1092.98   398.9 1089.93
   425.7  1084.3   439.9 1080.07   478.3 1067.34   494.5  1060.7   502.5 1058.43
   504.4 1057.92   517.5 1057.71   520.3 1057.69   541.2 1057.98   589.8 1060.24
   645.5 1061.75   658.1 1062.75   666.8 1064.37     739 1084.89   753.5 1088.58
   794.6 1097.42   811.7 1102.05   883.4 1128.54   979.2 1152.77    1012 1160.24
#Mann= 3 , 0 , 0
       0      .1       0   502.5    .045       0   517.5      .1       0
Bank Sta=502.5,517.5
XS Rating Curve= 0 ,0
Exp/Cntr=0.3,0.1

Type RM Length L Ch R = 1 ,7823.8  ,467.43,475.197,474.269
XS GIS Cut Line= 3
     1757883.567      251035.643     1757806.729       251524.67
       1757541.8      251987.762
#Sta/Elev= 30
       0 1123.49    42.9 1118.19      75  1114.9     115 1111.28     139 1107.95
   155.6 1104.94     210 1094.16   223.1 1092.06   235.2 1090.49   247.2 1089.38
   259.2 1087.49   283.2 1078.34   295.3 1076.46   307.3 1076.51   319.3 1075.94
     397 1069.73   415.4 1067.57   475.5 1058.23   487.5  1057.7     495 1057.68
   502.5 1057.68   578.2  1057.8   760.1 1061.83   801.1 1063.07   814.8 1065.28
   908.8 1087.55   937.9  1093.8     961 1098.23   980.7 1101.02  1028.5 1109.54
#Mann= 3 , 0 , 0
       0      .1       0   487.5    .045       0   502.5      .1       0
Bank Sta=487.5,502.5
XS Rating Curve= 0 ,0
Exp/Cntr=0.3,0.1

Type RM Length L Ch R = 1 ,7348.6  ,316.911,324.803,331.431
XS GIS Cut Line= 3
     1757746.597      250970.414     1757424.604      251269.727
     1757145.461      251774.007
#Sta/Elev= 30
       0 1123.67    18.1 1124.38    66.8 1124.62    77.1 1123.83   131.6 1117.22
   147.8 1113.75   212.7 1095.79   228.9 1091.02   245.1 1087.66   261.9 1085.15
   280.1 1080.61   297.5 1076.74   326.1  1071.4   374.8 1063.71   402.1  1058.7
   423.4 1055.23   439.6 1053.77   498.5 1051.91   513.1 1051.81   513.5 1051.81
   600.4 1052.28   641.1 1053.02   681.9 1054.84   761.5 1060.37   787.7  1063.9
   805.2 1067.07   813.9 1068.99   858.3 1080.13   939.7 1097.96    1016 1110.86
#Mann= 3 , 0 , 0
       0      .1       0   498.5    .045       0   513.5      .1       0
Bank Sta=498.5,513.5
XS Rating Curve= 0 ,0
Exp/Cntr=0.3,0.1

Type RM Length L Ch R = 1 ,7023.8  ,414.432,400,387.594
XS GIS Cut Line= 3
     1757556.795      250749.205     1757184.215      251081.426
      1756824.65        251440.2
#Sta/Elev= 30
       0 1171.98      49 1151.57    65.7  1143.5    81.6 1136.51   101.6 1129.86
   119.4 1126.01   155.1 1121.47   161.2 1120.19   177.1 1115.48   217.2 1101.99
   272.5 1088.46   333.5 1076.73   360.1 1074.21   369.1 1073.04   385.3 1067.81
   404.8 1059.51     419 1055.38   440.5  1053.4   463.4 1052.02   491.7 1049.76
   503.1 1049.43   506.7 1049.48   645.6  1051.1   738.1  1054.2   889.2  1061.7
   914.3 1063.21   931.1 1064.82   973.2  1069.8     990 1071.37  1007.1 1072.43
#Mann= 3 , 0 , 0
       0      .1       0   491.7    .045       0   506.7      .1       0
Bank Sta=491.7,506.7
XS Rating Curve= 0 ,0
Exp/Cntr=0.3,0.1

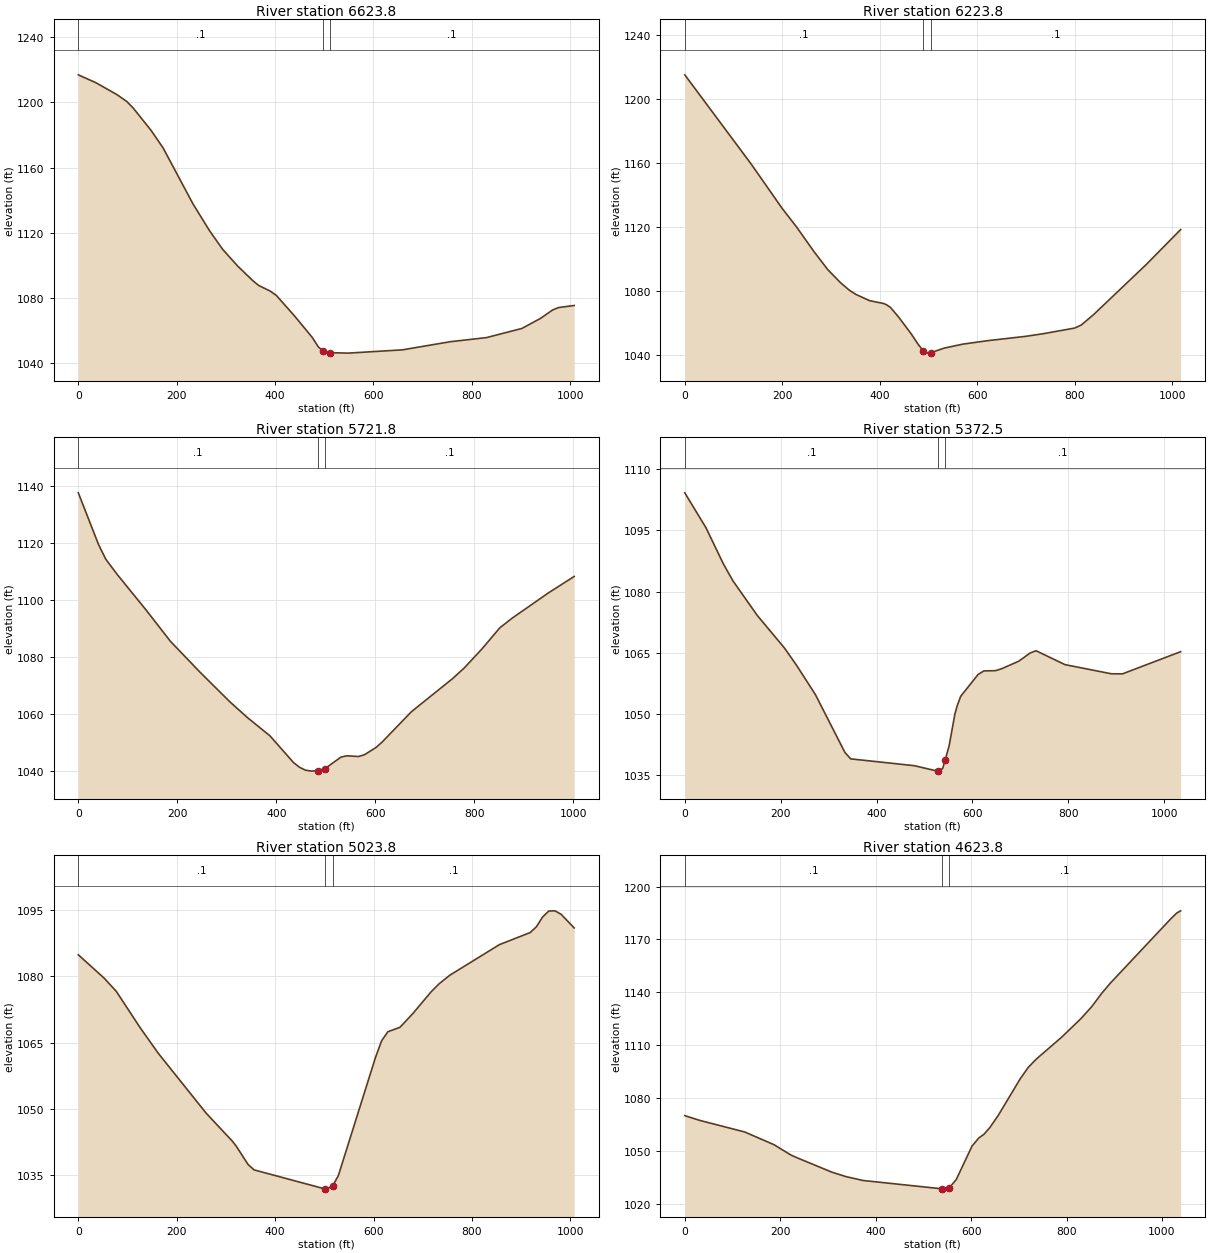
Type RM Length L Ch R = 1 ,6623.8  ,391.409,400,403.147
XS GIS Cut Line= 3
     1756945.229      250398.818     1756841.426      250892.588
     1756721.436      251381.779
#Sta/Elev= 30
       0 1216.97    35.9  1212.1    78.5 1204.83    98.5 1200.61   111.7 1196.56
   148.1  1182.8   172.3 1172.15     233 1137.84   266.7 1121.34   293.7 1109.78
   324.4 1099.49   354.3 1090.78   366.5 1087.73   390.7 1084.14   402.8 1081.53
   439.9 1068.89   475.6 1055.83   487.8 1050.07   497.1 1047.44   499.9 1046.63
   512.1 1046.42   548.4 1046.15   658.8 1048.15   756.6 1053.17   829.9 1055.67
   902.1  1061.3     940 1067.49   964.4 1072.63   976.6 1074.13  1008.3 1075.38
#Mann= 3 , 0 , 0
       0      .1       0   497.1    .045       0   512.1      .1       0
Bank Sta=497.1,512.1
XS Rating Curve= 0 ,0
Exp/Cntr=0.3,0.1

Type RM Length L Ch R = 1 ,6223.8  ,513.515,501.933,495.109
XS GIS Cut Line= 3
     1756768.028       250299.33     1756492.704      250713.149
     1756298.848      251195.775
#Sta/Elev= 30
       0 1215.06   136.7 1159.02   199.4 1131.64   229.3 1119.87     265 1104.46
   293.5 1093.13   319.2  1085.1   336.4 1080.58   350.6 1077.75   379.2 1073.77
   407.6 1072.02   413.4 1071.28   421.9 1069.57   439.1 1063.33   464.7 1052.91
   478.9 1046.38   489.5 1042.26   493.2 1041.51   499.2 1040.96   504.5  1041.2
     532 1044.09   570.3 1046.59   621.5 1048.76   698.3 1051.42   736.2 1053.16
   799.9 1056.65   813.4 1058.58     839 1065.18   946.5 1096.37  1017.1 1118.24
#Mann= 3 , 0 , 0
       0      .1       0   489.5    .045       0   504.5      .1       0
Bank Sta=489.5,504.5
XS Rating Curve= 0 ,0
Exp/Cntr=0.3,0.1

Type RM Length L Ch R = 1 ,5721.8  ,346.31,349.32,351.968
XS GIS Cut Line= 3
     1756020.561      250179.402     1756023.515      250705.249
      1756041.24      251180.874
#Sta/Elev= 30
       0 1137.69    40.9 1119.49    55.6 1114.33    79.4 1108.82   136.4 1096.63
   186.2 1085.49   245.6 1074.71   306.3 1064.24   341.7  1058.7   387.2 1052.29
   434.9 1042.88   446.9 1041.24   458.8 1040.23   471.2 1039.89   483.4 1040.09
   498.4 1040.76   530.5 1044.81   542.4 1045.28   566.2 1045.03   578.1 1045.64
   601.8 1048.24   613.7 1050.09   673.1 1060.79   756.3 1072.42     780 1076.19
   815.7 1082.87   851.5 1090.23   876.1 1093.59   950.2 1102.57  1001.8  1108.3
#Mann= 3 , 0 , 0
       0      .1       0   483.4    .045       0   498.4      .1       0
Bank Sta=483.4,498.4
XS Rating Curve= 0 ,0
Exp/Cntr=0.3,0.1

Type RM Length L Ch R = 1 ,5372.5  ,347.887,348.747,352.143
XS GIS Cut Line= 3
     1755788.637      250203.442     1755697.613      250691.714
     1755595.928      251219.845
#Sta/Elev= 30
       0 1104.17    44.2 1095.62    80.4  1086.8   100.4 1082.63   151.3 1074.15
   207.7 1066.23   232.8 1062.03   272.5 1054.79   334.1 1040.63   346.1 1039.06
     479 1037.39   527.3 1036.06     528  1036.1     538 1036.68     543 1038.71
   551.5 1042.24   563.6 1050.06   568.4 1052.08   575.7 1054.38     612 1059.72
   624.1 1060.59   648.2 1060.64   661.3 1061.13   696.6 1062.95   720.8 1064.99
   732.9 1065.52   793.3 1062.12   890.1 1059.88   913.1 1059.86  1034.5 1065.29
#Mann= 3 , 0 , 0
       0      .1       0     528    .045       0     543      .1       0
Bank Sta=528,543
XS Rating Curve= 0 ,0
Exp/Cntr=0.3,0.1

Type RM Length L Ch R = 1 ,5023.8  ,393.167,400,408.647
XS GIS Cut Line= 3
      1755483.64      250136.097     1755370.142       250632.53
     1755205.294      251103.833
#Sta/Elev= 30
       0  1084.9    52.8 1079.57    77.1 1076.62   125.8 1068.35   162.4 1062.59
   259.8 1049.01   312.9 1042.68   320.7 1041.57   345.1 1037.36   357.2 1036.16
   501.7 1031.83   503.4  1031.8   516.7  1032.5   528.4 1034.86   603.8 1061.62
   616.4 1065.43     629 1067.46   653.5 1068.46   679.3 1071.52     717 1076.52
   732.9  1078.3   754.8 1080.26   855.4 1087.18   918.3 1089.94   930.9 1091.25
   943.4 1093.45     956 1094.81   968.6 1094.86   981.2 1094.07  1007.6 1090.99
#Mann= 3 , 0 , 0
       0      .1       0   501.7    .045       0   516.7      .1       0
Bank Sta=501.7,516.7
XS Rating Curve= 0 ,0
Exp/Cntr=0.3,0.1

Type RM Length L Ch R = 1 ,4623.8  ,388.749,400,408.725
XS GIS Cut Line= 3
     1755267.723      250078.379     1754992.463      250550.867
      1754668.36      250921.463
#Sta/Elev= 30
       0 1070.01    31.4 1067.32   125.7 1060.74   186.9 1053.53   222.5 1047.66
   236.3 1045.99   308.4 1037.92     338  1035.4   373.7 1033.21   539.3 1028.48
   542.9 1028.31   551.4  1028.5   554.3 1029.12   568.9 1033.74   601.9 1052.71
   616.2 1057.36   627.1 1059.47   639.6 1063.36   657.7  1070.5   702.9 1090.91
   719.7 1097.38   736.5 1102.08   789.7 1114.54     830 1125.03   852.8 1131.86
   874.1 1139.56   892.1 1145.31  1018.4 1181.69    1031 1185.02  1039.1 1186.26
#Mann= 3 , 0 , 0
       0      .1       0   539.3    .045       0   554.3      .1       0
Bank Sta=539.3,554.3
XS Rating Curve= 0 ,0
Exp/Cntr=0.3,0.1

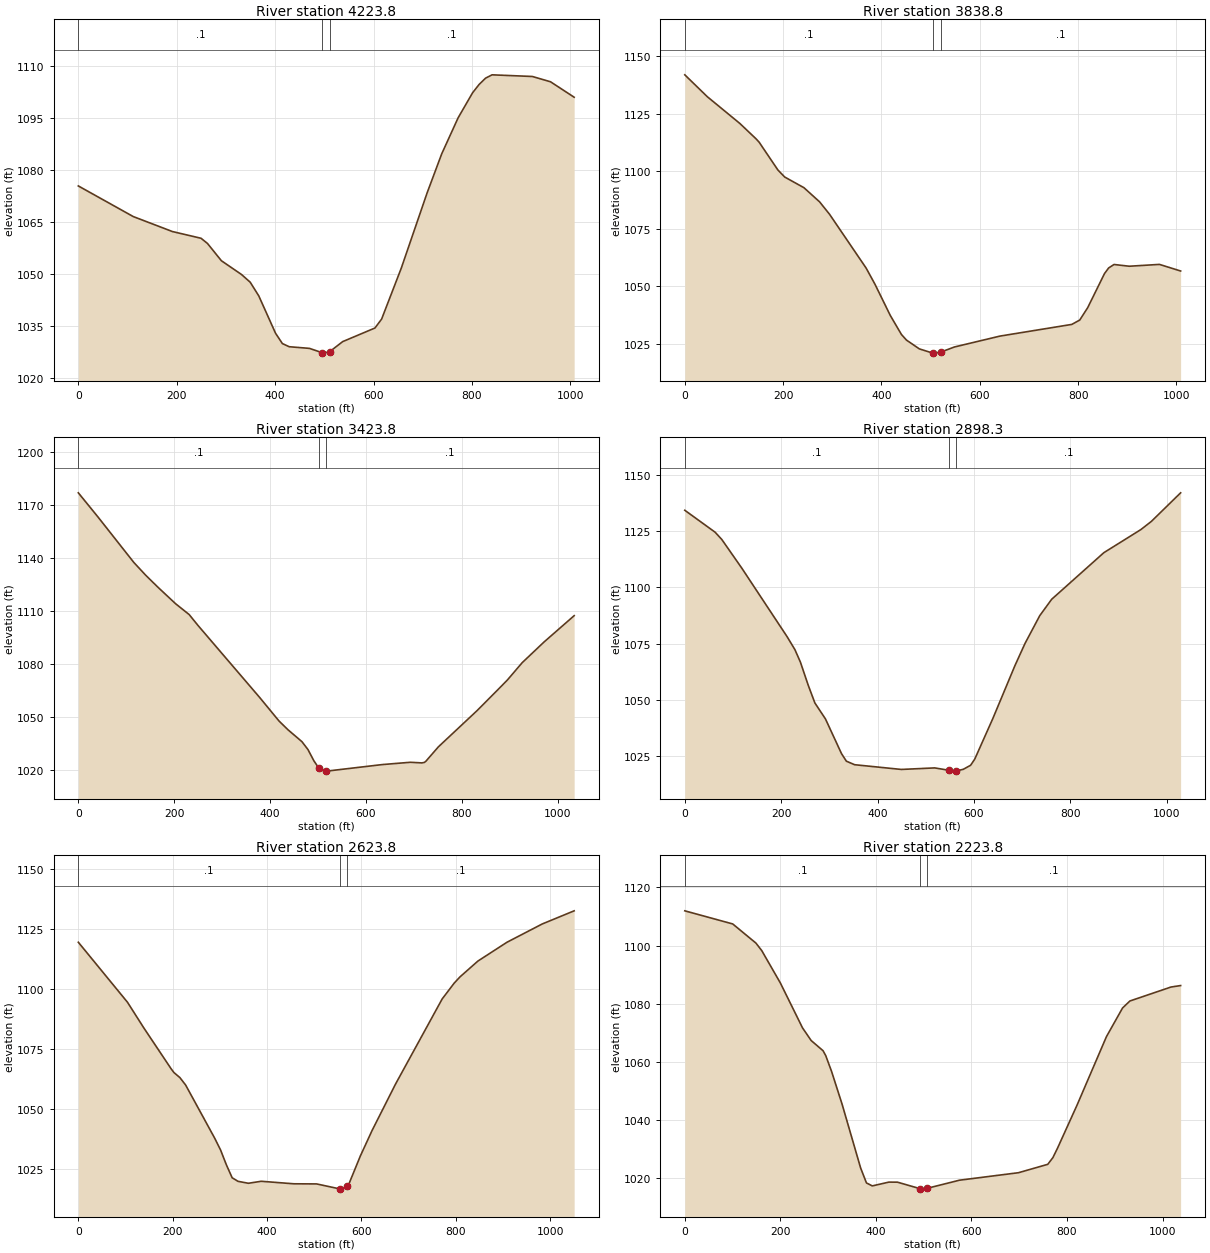
Type RM Length L Ch R = 1 ,4223.8  ,382.213,384.931,384.398
XS GIS Cut Line= 3
     1755193.747      249995.537     1754760.012      250250.935
     1754306.449       250471.42
#Sta/Elev= 30
       0 1075.46   111.6 1066.62   191.2 1062.29   249.4 1060.35   262.5 1058.85
   290.7 1053.87   331.6 1049.89   349.2 1047.68   366.6 1043.75   400.9  1032.9
   414.7 1029.94   428.5 1029.03   469.8 1028.55   495.8 1027.29   497.4 1027.18
   510.8 1027.59   537.2  1030.5   602.8 1034.43   616.4 1037.01   656.4 1051.74
   708.8 1073.43   738.5 1084.72   771.9 1095.14   801.3 1102.37   814.5 1104.76
   827.7 1106.59   840.9 1107.55   922.9 1107.07   959.7 1105.54  1007.7 1101.08
#Mann= 3 , 0 , 0
       0      .1       0   495.8    .045       0   510.8      .1       0
Bank Sta=495.8,510.8
XS Rating Curve= 0 ,0
Exp/Cntr=0.3,0.1

Type RM Length L Ch R = 1 ,3838.8  ,413.733,415.069,408.138
XS GIS Cut Line= 3
     1755069.034       249706.49     1754527.488      249951.575
      1754245.53      250254.679
#Sta/Elev= 30
       0 1141.89    45.9 1132.35     112 1120.73   144.6 1114.11   151.1 1112.61
   189.4 1100.48   203.2 1097.43   242.3 1092.79   274.1 1086.64   294.5  1081.2
   368.9 1057.78   386.8 1050.78     418 1037.18   440.6 1028.94   450.8  1026.5
   476.9 1022.68   504.4 1020.82   505.3 1020.82   520.3 1021.24   548.3 1023.49
     641 1028.23     787 1033.31   803.2  1035.2   819.4 1040.59   853.6 1055.43
     862 1057.87     873 1059.38     904 1058.62   965.3 1059.42  1008.4 1056.55
#Mann= 3 , 0 , 0
       0      .1       0   505.3    .045       0   520.3      .1       0
Bank Sta=505.3,520.3
XS Rating Curve= 0 ,0
Exp/Cntr=0.3,0.1

Type RM Length L Ch R = 1 ,3423.8  ,538.617,525.508,521.355
XS GIS Cut Line= 3
     1754886.825      249411.206     1754404.603      249572.772
     1753976.298      249877.301
#Sta/Elev= 30
       0 1177.15    40.7 1163.57   115.8 1137.71   140.8 1130.42   166.8  1123.5
   202.9 1114.35   231.1 1108.24   249.8 1101.99   378.8 1061.08   418.6 1047.94
   437.4 1042.96   466.4 1036.24   478.9  1031.8   491.4 1025.36   501.1 1021.45
     504 1020.28   516.1 1019.64   517.8 1019.57   634.3 1023.29   692.6 1024.58
   716.4 1024.23   721.7  1024.5   724.9 1025.18   750.9 1033.31   831.9  1053.9
     882  1067.6   895.2 1071.28   925.7 1080.97   971.8 1092.81  1034.1 1107.59
#Mann= 3 , 0 , 0
       0      .1       0   501.1    .045       0   516.1      .1       0
Bank Sta=501.1,516.1
XS Rating Curve= 0 ,0
Exp/Cntr=0.3,0.1

Type RM Length L Ch R = 1 ,2898.3  ,260.545,274.492,287.749
XS GIS Cut Line= 3
     1754475.103      248987.248     1754029.878      249250.417
     1753705.594      249645.885
#Sta/Elev= 30
       0 1134.31      63 1124.54    76.8 1121.32   118.2 1108.61   212.3 1078.12
   228.5 1072.36   239.8 1066.86   256.1 1056.54   269.9 1048.68   291.8  1041.6
   325.1 1026.18   335.2 1022.82   352.3 1021.25   449.2 1019.15   518.5 1019.83
   548.2 1018.77   559.4  1018.4   563.2  1018.5   577.6 1019.19   592.9    1021
   601.6 1023.78     639 1041.75     685 1065.34   705.7  1075.1   736.5 1087.53
   761.2 1094.78   869.3 1115.46     946 1125.71   967.9 1129.36  1028.6 1142.06
#Mann= 3 , 0 , 0
       0      .1       0   548.2    .045       0   563.2      .1       0
Bank Sta=548.2,563.2
XS Rating Curve= 0 ,0
Exp/Cntr=0.3,0.1

Type RM Length L Ch R = 1 ,2623.8  ,400.04,400,399.813
XS GIS Cut Line= 3
     1754414.365      248893.824     1753873.789      249044.917
     1753406.361      249191.159
#Sta/Elev= 30
       0 1119.48   104.2 1094.48   138.9 1083.76   196.6 1066.79   202.8 1065.16
   215.2  1063.1   227.5 1059.98   289.1 1037.83   301.5 1032.94   313.8 1026.76
   326.1 1021.35   338.5 1019.86   360.5 1019.05   387.8 1019.88   456.9 1018.83
   505.1 1018.78   553.8 1016.72   560.3 1016.61   568.8 1017.76   572.8 1018.37
   597.7 1030.35   622.5 1040.95   672.3 1060.33   771.3 1095.85   796.7 1102.42
   809.1 1105.05   847.1 1111.64   908.7 1119.48   983.3 1127.08  1051.1 1132.57
#Mann= 3 , 0 , 0
       0      .1       0   553.8    .045       0   568.8      .1       0
Bank Sta=553.8,568.8
XS Rating Curve= 0 ,0
Exp/Cntr=0.3,0.1

Type RM Length L Ch R = 1 ,2223.8  ,757.224,753.455,747.721
XS GIS Cut Line= 3
     1754364.399      248586.141     1753876.999      248695.587
     1753356.509      248832.218
#Sta/Elev= 30
       0 1111.93   100.3 1107.42     149 1100.82   161.2 1098.22     200 1087.13
   246.4 1071.69   264.5 1067.34   289.4 1063.83     295 1062.14   307.2 1056.72
   329.2 1045.46     368 1023.53   380.2 1018.39   392.4 1017.37   427.1 1018.67
   445.1 1018.65     492 1016.43   498.1 1016.26     507 1016.53   574.9 1019.33
   698.3  1021.9   759.7 1024.79   770.4  1027.1   780.1 1030.35   821.1  1045.2
   882.4 1068.66   916.2 1078.53   931.5 1080.93  1017.5 1085.73  1037.7 1086.24
#Mann= 3 , 0 , 0
       0      .1       0     492    .045       0     507      .1       0
Bank Sta=492,507
XS Rating Curve= 0 ,0
Exp/Cntr=0.3,0.1

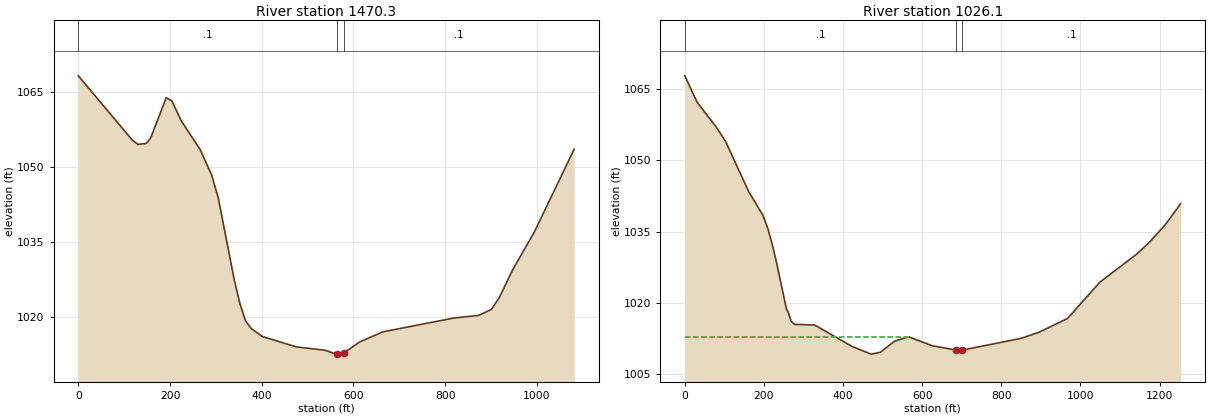
Type RM Length L Ch R = 1 ,1470.3  ,448.354,444.221,439.384
XS GIS Cut Line= 3
     1754189.521      248039.223     1753659.331      248192.189
     1753164.499      248380.244
#Sta/Elev= 30
       0  1068.2   117.6 1055.36     130  1054.5   148.3 1054.69   157.9 1055.82
   191.7 1063.82   204.1 1063.17     225 1059.11   265.9 1053.42   290.6  1048.4
   305.1 1043.82     340 1027.42   352.4 1022.66   364.7 1019.22   377.1 1017.67
   401.8 1016.07   475.9    1014   537.7 1013.36   562.7 1012.57   563.5 1012.58
   578.5 1012.77   613.5 1015.01   664.3 1017.03     818 1019.77   873.2 1020.32
   900.8  1021.5   918.4 1023.95   946.9 1029.39   994.6 1037.02  1081.2 1053.54
#Mann= 3 , 0 , 0
       0      .1       0   563.5    .045       0   578.5      .1       0
Bank Sta=563.5,578.5
XS Rating Curve= 0 ,0
Exp/Cntr=0.3,0.1

Type RM Length L Ch R = 1 ,1026.1  ,1000.189,1026.103,1049.508
XS GIS Cut Line= 3
     1754155.325      247876.817     1753501.646       247902.62
     1753011.386      248246.662
#Sta/Elev= 30
       0 1067.78    31.3 1062.22    78.9 1057.08   102.6 1054.07     162 1043.35
   197.3 1038.51   209.6 1035.75   221.4 1032.19   231.6 1028.65   257.1 1018.67
   259.9 1018.43     269 1016.18   277.3 1015.54   328.4 1015.39   423.4 1010.86
     471 1009.28   494.5 1009.68   530.4 1012.01     566 1012.92   625.4 1011.04
   686.6 1010.12   701.6 1010.13   849.6 1012.59   894.7 1013.86   967.2 1016.77
  1049.4 1024.43  1141.2 1030.24  1174.4 1032.81  1213.7 1036.41  1253.1 1040.89
#Mann= 3 , 0 , 0
       0      .1       0   686.6    .045       0   701.6      .1       0
#XS Ineff= 2 , 0
          566.29 1012.97
Permanent Ineff=
       F       F
Bank Sta=686.6,701.6
XS Rating Curve= 0 ,0
Exp/Cntr=0.3,0.1

Chan Stop Cuts=-1
Use User Specified Reach Order=0